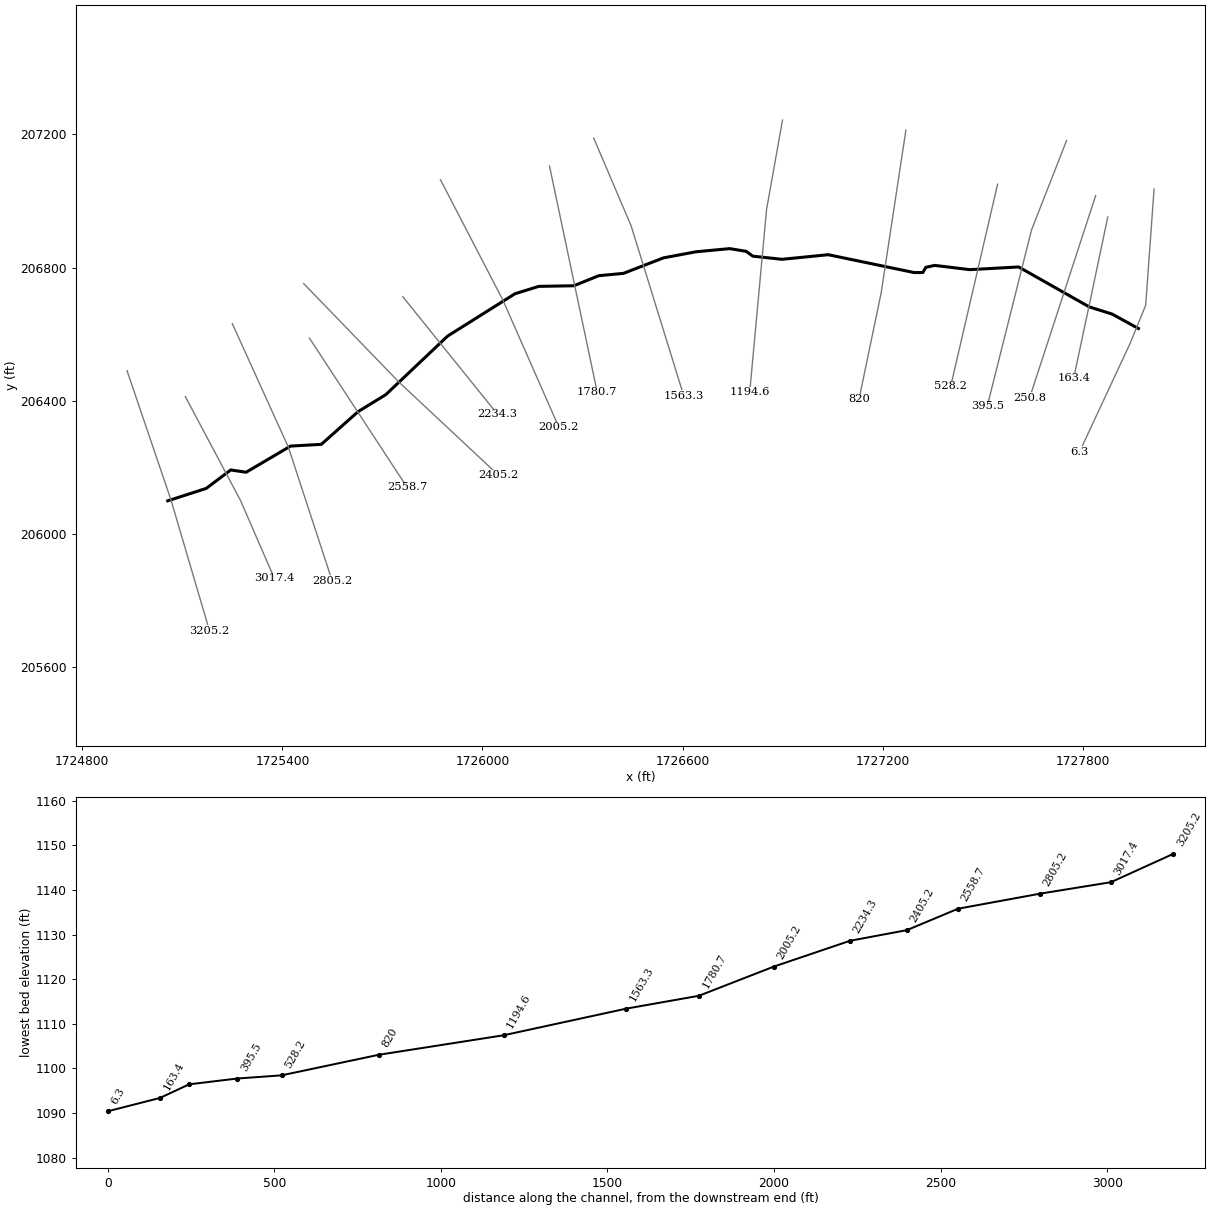
--- TraceFk1.prj (project) ---

Proj Title=TraceFk1
Current Plan=p01
Default Exp/Contr=0,0
English Units
Geom File=g01
Flow File=f01
Plan File=p01
BEGIN DESCRIPTION:
END DESCRIPTION:
DSS Export Rating Curves= 0
DSS Export Rating Curve Sorted= 0
DSS Export Volume Flow Curves= 0
DXF OffsetX= 0
DXF OffsetY= 0
DXF ScaleX= 0
DXF ScaleY= 0

--- TraceFk1.p01 (plan) ---

Plan Title=Floodplain
Program Version=4.00
Geom File=g01
Flow File=f01
K Sum by GR=0
Std Step Tol=0.01
Critical Tol=0.01
Num of Std Step Trials=20
Max Error Tol=0.3
Flow Tol Ratio=0.001
Split Flow NTrial=30
Split Flow Tol=0.02
Split Flow Ratio=0.02
Log Output Level=0
Friction Slope Method=1
Unsteady Friction Slope Method=2
Unsteady Bridges Friction Slope Method=1
Global Log Level=0
CheckData=False
Run HTab=0
Run UNet=0
Run PostProcess=0
UNET Theta=0
UNET Theta Warmup=0
UNET ZTol=0
UNET ZSATol=0
UNET MxIter=0
UNET MaxInSteps=0
UNET DtIC=0
UNET DtMin=0
UNET MaxCRTS=0
UNET WFStab=0
UNET SFStab=0
UNET WFX=0
UNET SFX=0
UNET DSS MLevel=0
UNET DZMax Abort=0
UNET Convert EG Bridges=0
UNET Use Existing IB Tables=0
UNET Froude Limit=0
UNET Froude Power=0
Write IC File=0
Echo Input=False
Echo Output=False
Write Detailed=0

--- TraceFk1.f01 (steady flow) ---

Flow Title=NFF Regression Equation
Program Version=4.00
Number of Profiles=1
Profile Names=P100yr
River Rch & RM=TraceFk1,Main      ,3205.2
553.3537
River Rch & RM=TraceFk1,Main      ,3205.2
352.3306
River Rch & RM=TraceFk1,Main      ,1780.7
584.6654
River Rch & RM=TraceFk1,Main      ,1780.7
376.1227
River Rch & RM=TraceFk1,Main      ,250.8
635.0201
River Rch & RM=TraceFk1,Main      ,250.8
412.1778
Boundary for River Rch & Prof#=TraceFk1,Main      ,1
Up Type=0
Dn Type=3
Dn Slope=0.019327

--- TraceFk1.g01 (geometry) ---

Geom Title=USGS 10m DEM
Program Version=4.00

River Reach=TraceFk1        ,Main
Reach XY= 30
     1725056.315      206099.995     1725171.609      206137.271
     1725245.307      206192.701     1725291.289      206185.772
      1725424.58      206264.383     1725516.791      206269.548
     1725627.023      206367.812     1725710.169      206418.834
     1725895.358      206594.574     1726097.555      206721.813
     1726168.733      206743.859     1726273.925      206745.749
     1726348.883      206775.984     1726422.581      206782.913
     1726542.891      206829.525     1726640.524      206847.792
     1726741.308      206857.241     1726790.439      206849.052
     1726810.596      206834.564     1726898.151      206825.116
     1727036.729      206838.974     1727293.726      206785.433
     1727320.181      206785.433      1727329.63       206801.18
     1727356.085      206806.849     1727461.255      206794.071
     1727607.657      206802.205     1727819.127      206682.372
      1727887.99      206660.683     1727966.796       206617.35

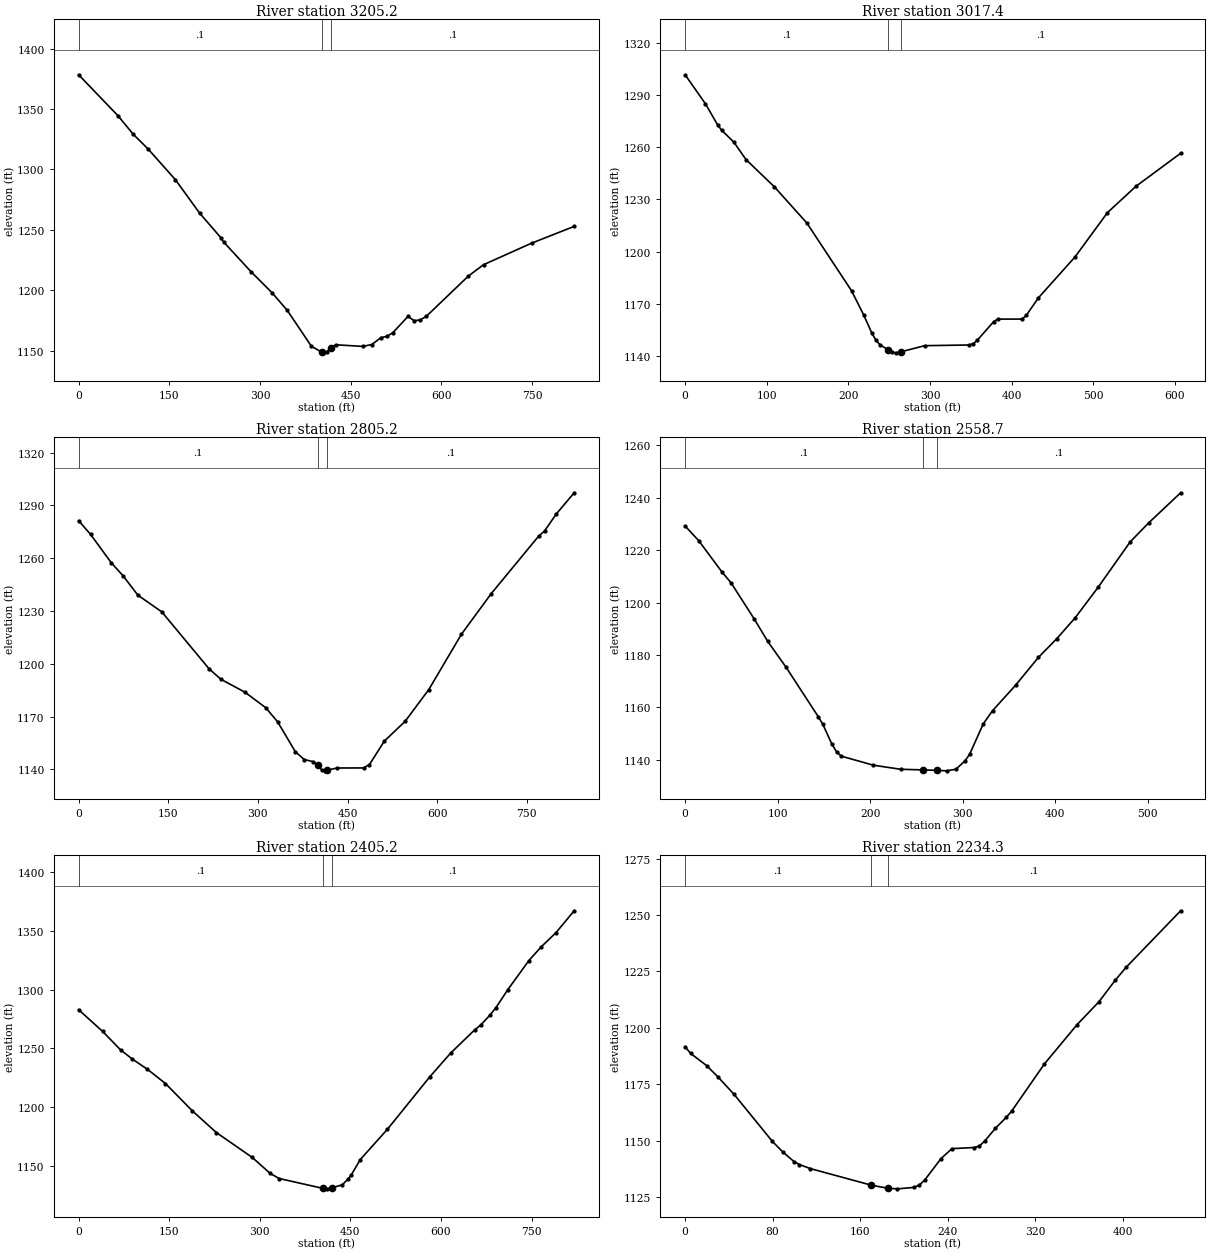
Type RM Length L Ch R = 1 ,3205.2  ,184.3,187.8,192.2
XS GIS Cut Line= 3
     1724934.172      206490.994     1725065.908      206102.816
       1725181.4      205710.017
#Sta/Elev= 30
       0 1378.38      65  1344.5      90 1329.28     115 1316.85     160 1291.51
     200 1263.84     235 1243.58     240 1239.81     285 1215.32   319.9 1197.82
   344.9 1183.33   384.9 1153.57   402.4 1148.54   404.9 1148.11   409.9 1148.82
   417.4 1152.33   424.9 1154.79   469.8 1153.46   484.8 1154.99   499.8 1160.67
   509.8 1161.77   519.8 1164.88   544.7 1178.32   554.7 1174.73   564.7 1175.35
   574.7 1178.24   644.6 1211.76   669.6 1221.12   749.4 1239.02   819.4 1252.81
#Mann= 3 , 0 , 0
       0      .1       0   402.4    .045       0   417.4      .1       0
Bank Sta=402.4,417.4
XS Rating Curve= 0 ,0
Exp/Cntr=0.3,0.1

Type RM Length L Ch R = 1 ,3017.4  ,213.8,212.2,208.2
XS GIS Cut Line= 3
     1725109.063      206412.814      1725274.57      206100.841
     1725375.632      205867.959
#Sta/Elev= 30
       0 1301.66    24.9 1285.01    39.8 1272.86    44.8 1269.76    59.7 1262.93
    74.6 1252.91   109.4 1237.19   149.2 1216.38   203.9 1177.42   218.9  1163.4
   228.8 1153.05   233.8 1149.02   238.8 1146.35     249 1143.42   253.7 1141.96
   258.6 1141.74     264  1142.3   293.5 1145.86   348.2 1146.26   353.2  1147.1
   358.1 1149.09     378 1159.68     383 1161.14   412.9 1161.16   417.9 1163.28
   432.8 1173.37   477.6 1196.88   517.4  1222.4   552.3 1237.54     607 1256.51
#Mann= 3 , 0 , 0
       0      .1       0     249    .045       0     264      .1       0
Bank Sta=249,264
XS Rating Curve= 0 ,0
Exp/Cntr=0.3,0.1

Type RM Length L Ch R = 1 ,2805.2  ,242.8,246.5,252.6
XS GIS Cut Line= 3
     1725249.869      206632.044     1725417.951       206261.08
     1725549.181      205860.034
#Sta/Elev= 30
       0 1281.35    19.9 1273.61    54.6 1257.46    74.5 1249.97    99.3 1238.97
   139.1 1229.56   218.5 1197.08   238.4 1191.15   278.1 1183.91   312.9 1175.12
   332.8 1167.13   362.6 1150.07   377.5  1145.6   392.4 1144.41   399.8 1142.37
   407.3 1139.47   412.2 1139.18   414.8 1139.45   432.1 1140.78   476.8 1140.84
   486.7 1142.78   511.5 1156.06   546.3 1167.31     586 1185.41   640.6 1216.84
   690.2 1239.82   769.7 1272.56   779.6  1275.5   799.4 1285.22   829.2 1297.22
#Mann= 3 , 0 , 0
       0      .1       0   399.8    .045       0   414.8      .1       0
Bank Sta=399.8,414.8
XS Rating Curve= 0 ,0
Exp/Cntr=0.3,0.1

Type RM Length L Ch R = 1 ,2558.7  ,149.2,153.5,158.9
XS GIS Cut Line= 2
     1725481.088      206588.574     1725774.021      206140.387
#Sta/Elev= 30
       0 1229.21    14.9 1223.53    39.7 1211.72    49.6 1207.56    74.4  1193.9
    89.2 1185.23   109.1 1175.32   143.8  1156.5   148.7 1153.61   158.6 1145.99
   163.6 1143.08   168.6 1141.42   203.3 1137.96     233 1136.39   257.4 1136.16
   272.4 1135.98   282.6  1135.8   292.5 1136.41   302.4 1139.57   307.4 1142.11
   322.2 1153.76   332.2 1158.75     357 1168.44   381.7 1179.06   401.6 1186.22
   421.4 1194.17   446.2  1205.8   480.9 1223.16   500.7 1230.34   535.4 1241.88
#Mann= 3 , 0 , 0
       0      .1       0   257.4    .045       0   272.4      .1       0
Bank Sta=257.4,272.4
XS Rating Curve= 0 ,0
Exp/Cntr=0.3,0.1

Type RM Length L Ch R = 1 ,2405.2  ,172.9,170.9,167.7
XS GIS Cut Line= 3
     1725463.943      206752.091      1725749.84      206456.136
     1726048.407      206176.497
#Sta/Elev= 30
       0 1282.87    39.7 1264.48    69.4 1248.84    89.2 1240.92     114 1232.33
   143.8 1220.29   188.4 1197.05   228.1 1178.71   287.6  1157.6   317.3 1144.01
   332.2 1139.74     404 1131.46   411.5    1131     419 1131.85   436.4 1134.39
   446.4 1139.36   451.4 1142.71   466.4 1155.83   511.3 1181.47   581.1 1225.72
     616 1246.06   655.9  1265.8   665.9  1269.9   680.9 1278.14   690.9 1284.48
   710.8 1299.97   745.7 1324.58   765.7 1336.01   790.6 1348.25   820.6 1366.74
#Mann= 3 , 0 , 0
       0      .1       0     404    .045       0     419      .1       0
Bank Sta=404,419
XS Rating Curve= 0 ,0
Exp/Cntr=0.3,0.1

Type RM Length L Ch R = 1 ,2234.3  ,233.6,229.1,223.1
XS GIS Cut Line= 2
     1725760.839       206713.07     1726044.984      206360.086
#Sta/Elev= 30
       0 1191.61       5 1188.67    19.9 1183.16    29.9  1178.3    44.8 1170.49
    79.7  1149.7    89.6 1144.81    99.6 1140.71   104.6 1139.37   114.5 1137.59
   170.3 1130.23   185.3 1128.88   194.2 1128.61   209.1 1129.23   214.1 1130.25
   219.1  1132.5     234 1142.03     244 1146.43   263.9 1146.92   268.9  1147.5
   273.9 1149.77   283.8 1155.49   293.8 1160.36   298.8 1163.21   328.6 1184.02
   358.5 1201.46   378.4 1211.54   393.4 1221.14   403.3 1226.85   453.1 1251.88
#Mann= 3 , 0 , 0
       0      .1       0   170.3    .045       0   185.3      .1       0
Bank Sta=170.3,185.3
XS Rating Curve= 0 ,0
Exp/Cntr=0.3,0.1

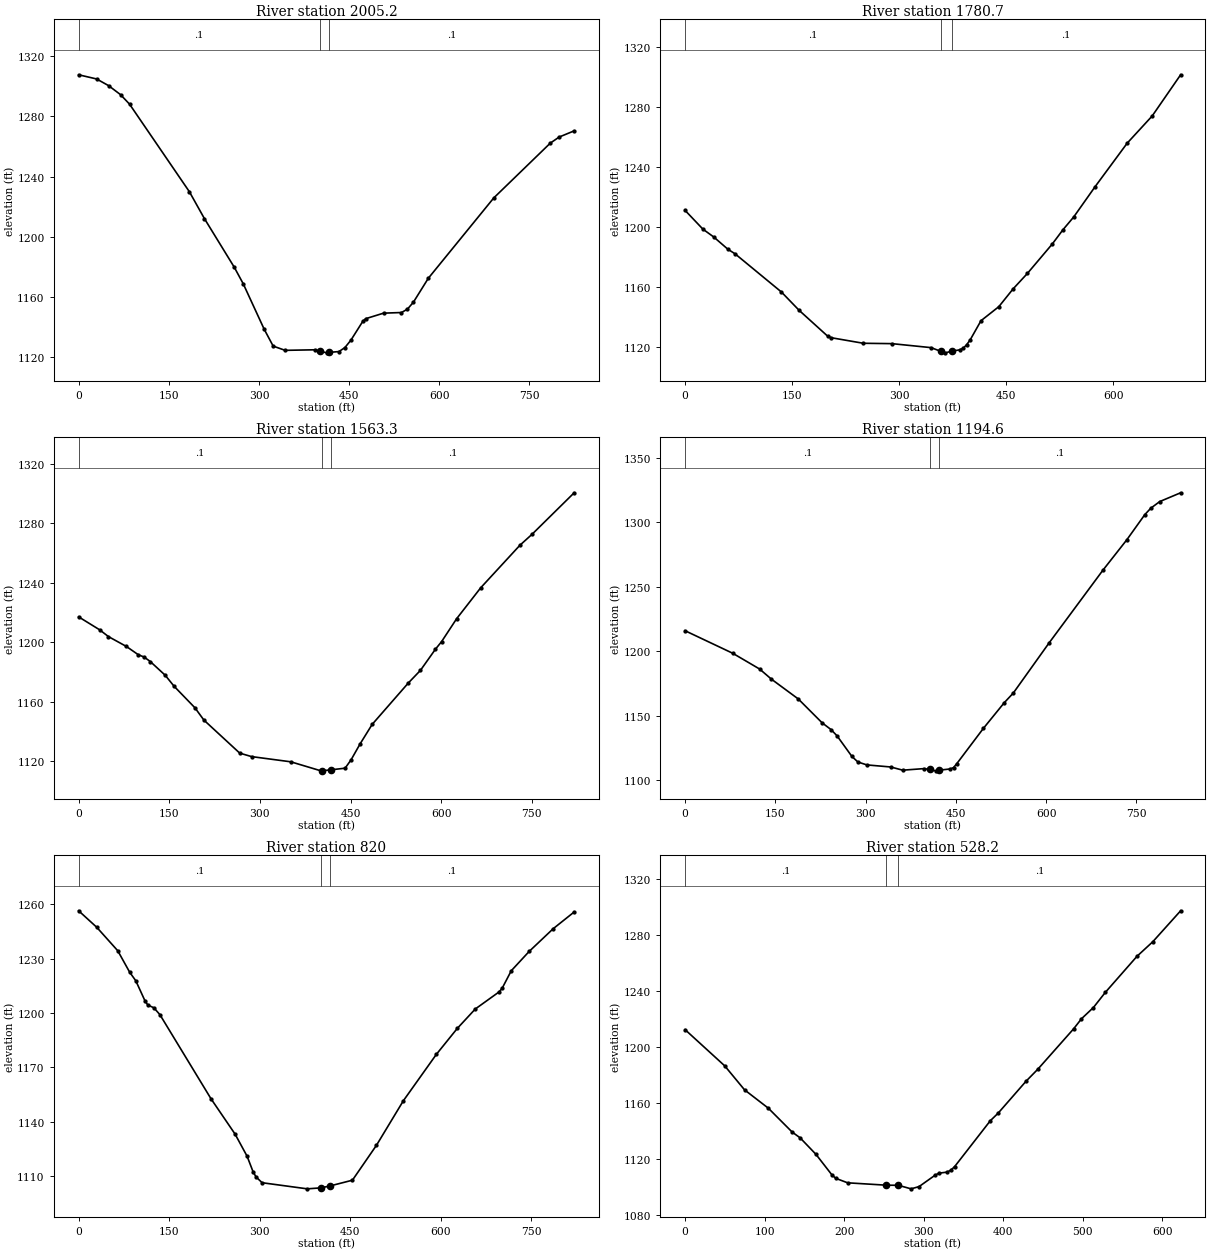
Type RM Length L Ch R = 1 ,2005.2  ,230.6,224.5,219.7
XS GIS Cut Line= 3
     1725873.746      207064.441     1726061.608      206701.843
     1726228.995      206320.876
#Sta/Elev= 30
       0 1307.61    29.9 1304.83    49.8  1300.4    69.7 1294.41    84.7 1288.09
   184.3 1229.87   209.2 1212.08     259 1179.68   273.9 1168.68   308.8 1138.44
   323.7 1127.28   343.6 1124.47   393.4 1124.84   400.9  1123.9   413.3 1122.81
   415.9 1123.09   433.1 1123.65     443 1126.29     453 1131.22   472.8 1143.74
   477.7 1145.52   507.4 1149.19   537.2  1149.6   547.1 1151.86     557 1156.46
   581.8 1172.36   690.7 1225.76   784.9 1262.23   799.7 1266.26   824.5 1270.34
#Mann= 3 , 0 , 0
       0      .1       0   400.9    .045       0   415.9      .1       0
Bank Sta=400.9,415.9
XS Rating Curve= 0 ,0
Exp/Cntr=0.3,0.1

Type RM Length L Ch R = 1 ,1780.7  ,215.2,217.4,219.7
XS GIS Cut Line= 2
     1726200.889      207105.356     1726344.101      206425.752
#Sta/Elev= 30
       0 1211.03      25 1198.54      40  1193.4      60 1185.19      70 1182.16
   134.9 1156.79   159.9 1144.52   199.9 1127.33   204.9 1126.33   249.8 1122.64
   289.8  1122.4   344.8 1119.74   358.9 1117.18   364.8 1116.28   373.9 1117.43
   384.7 1118.25   389.7 1119.33   394.7 1121.72   399.7 1125.04   414.7 1137.65
   439.7    1147   459.7 1158.82   479.7 1169.08   514.6 1188.67   529.6 1198.18
   544.6 1206.63   574.6  1226.8   619.6 1255.76   654.6 1273.83   694.5 1301.25
#Mann= 3 , 0 , 0
       0      .1       0   358.9    .045       0   373.9      .1       0
Bank Sta=358.9,373.9
XS Rating Curve= 0 ,0
Exp/Cntr=0.3,0.1

Type RM Length L Ch R = 1 ,1563.3  ,377.4,368.7,360.1
XS GIS Cut Line= 3
     1726333.529      207189.126     1726445.651      206925.691
     1726603.401      206415.746
#Sta/Elev= 30
       0 1216.96    34.6  1208.3    49.4 1203.68      79 1197.07    98.7 1191.51
   108.6 1189.89   118.5 1186.94   143.2 1177.73     158 1170.29   192.5  1155.8
   207.3 1147.55   266.6 1125.32   286.3 1122.98   351.2 1119.48     401 1113.41
   402.7 1113.42   417.7 1114.11     441 1115.19   450.9 1120.83   465.9 1131.59
   485.8 1144.65   545.7 1172.52   565.7 1180.99   590.6 1195.27   600.6 1200.26
   625.5 1215.68   665.4 1236.51   730.3 1265.12   750.2 1272.42   820.1 1300.41
#Mann= 3 , 0 , 0
       0      .1       0   402.7    .045       0   417.7      .1       0
Bank Sta=402.7,417.7
XS Rating Curve= 0 ,0
Exp/Cntr=0.3,0.1

Type RM Length L Ch R = 1 ,1194.6  ,376,374.6,373.3
XS GIS Cut Line= 3
     1726899.594      207243.204     1726851.851      206975.164
     1726801.222      206426.151
#Sta/Elev= 30
       0 1216.01    79.2 1198.54   123.8 1186.35   143.6 1178.44   188.1 1163.14
   227.7 1144.66   242.6 1139.38   252.5 1134.59   277.2 1118.62   287.2 1114.28
   302.1 1112.02   341.8 1110.42   361.7 1107.94   396.4 1109.13   407.1 1108.52
   416.3 1107.43   422.1 1107.93   441.1 1108.92   446.1 1109.95   451.1 1112.71
   495.8 1140.36   530.5 1160.27   545.4 1167.68     605  1206.6   694.5 1262.98
   734.2 1286.52     764 1305.96   773.9 1310.93   788.8 1316.11   823.6 1322.93
#Mann= 3 , 0 , 0
       0      .1       0   407.1    .045       0   422.1      .1       0
Bank Sta=407.1,422.1
XS Rating Curve= 0 ,0
Exp/Cntr=0.3,0.1

Type RM Length L Ch R = 1 ,820     ,292.7,291.7,290.2
XS GIS Cut Line= 3
     1727269.536      207213.067     1727195.559      206725.194
      1727128.86      206404.531
#Sta/Elev= 30
       0 1256.38    29.9 1247.32    64.8 1234.35    84.7 1222.43    94.7  1217.8
   109.7 1206.88   114.6  1204.4   124.6  1202.9   134.6 1199.12   219.3 1152.73
   259.2 1133.24   279.1 1121.05   289.1  1112.4   294.1 1109.56     304 1106.43
   378.8 1103.06   401.6  1103.6   416.6 1104.67   453.6 1107.82   493.4 1127.05
   538.1 1151.68   592.7 1177.22   627.4 1191.54   657.2 1202.23   696.9 1211.72
   701.9  1213.8   716.8 1223.32   746.5 1233.99   786.2 1246.48     821 1255.72
#Mann= 3 , 0 , 0
       0      .1       0   401.6    .045       0   416.6      .1       0
Bank Sta=401.6,416.6
XS Rating Curve= 0 ,0
Exp/Cntr=0.3,0.1

Type RM Length L Ch R = 1 ,528.2   ,132.9,132.7,132.5
XS GIS Cut Line= 2
     1727544.474      207050.675     1727403.866      206443.979
#Sta/Elev= 30
       0 1212.34    49.8 1186.45    74.7 1169.29   104.6 1156.16   134.5 1139.11
   144.5 1134.98   164.4 1123.18   184.3  1108.6   189.3 1105.97   204.3 1102.76
     253 1101.06     268 1100.99     284 1098.45     294 1100.04   313.9 1108.08
   318.9 1109.67   328.8 1110.37   333.8 1111.71   338.8 1114.39   383.6 1147.18
   393.6  1152.7   428.5 1175.45   443.4  1184.1   488.3 1212.94   498.2 1220.15
   513.2  1228.2   528.1 1238.99     568 1264.87   587.9 1275.31   622.8 1297.41
#Mann= 3 , 0 , 0
       0      .1       0     253    .045       0     268      .1       0
Bank Sta=253,268
XS Rating Curve= 0 ,0
Exp/Cntr=0.3,0.1

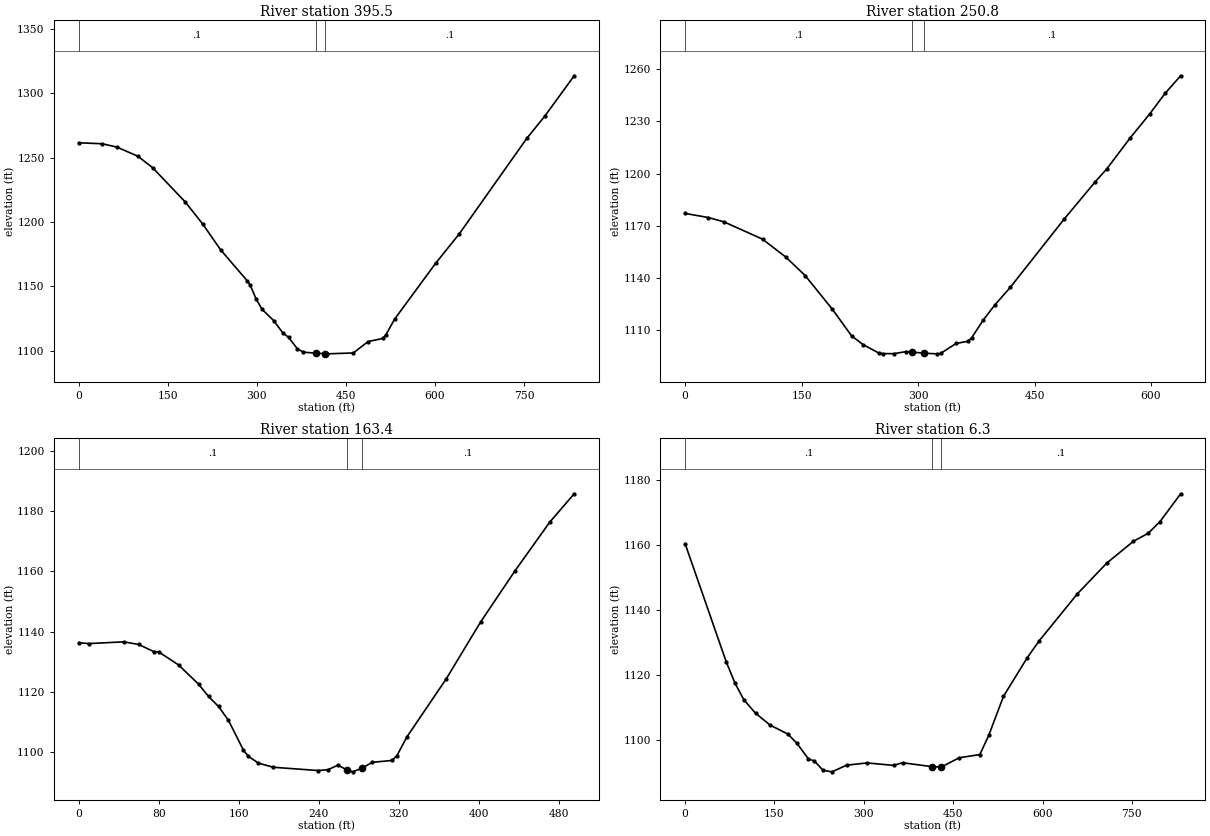
Type RM Length L Ch R = 1 ,395.5   ,146.1,144.7,143.2
XS GIS Cut Line= 3
     1727751.296      207181.742     1727646.024      206912.671
     1727513.339       206383.64
#Sta/Elev= 30
       0 1261.53    39.8 1260.75    64.8 1258.14    99.6 1251.11   124.5 1242.22
   179.3 1215.71   209.2 1198.34   239.1 1178.44     284 1154.34   288.9 1151.03
   298.8 1140.37   308.8 1132.33   328.6 1123.46   343.5 1114.17   353.4 1110.56
   368.3 1101.69   378.2 1099.06   399.6 1098.24   414.6 1097.89   417.8 1097.74
   462.5 1098.41   487.3 1107.24   512.1  1109.7     517 1112.21   531.9 1124.56
   601.3  1168.1     641 1190.88     755 1265.18   784.8 1282.13   834.4 1313.52
#Mann= 3 , 0 , 0
       0      .1       0   399.6    .045       0   414.6      .1       0
Bank Sta=399.6,414.6
XS Rating Curve= 0 ,0
Exp/Cntr=0.3,0.1

Type RM Length L Ch R = 1 ,250.8   ,84.7,87.4,89.7
XS GIS Cut Line= 2
     1727838.709      207016.825     1727640.817      206410.129
#Sta/Elev= 30
       0 1177.16    29.9  1174.8    49.9 1172.34    99.7 1162.36   129.6 1152.11
   154.6 1141.44   189.4 1122.22   214.4 1106.78   229.3 1101.72   249.3 1096.94
   254.3 1096.58   269.2 1096.53   284.2 1097.72   292.5 1097.45   307.5 1096.81
   324.1 1096.44     329 1096.64     349  1102.4     364 1103.64   368.9 1105.54
   383.9 1115.82   398.8 1124.47   418.8 1134.66   488.6 1174.13   528.5 1195.48
   543.4 1202.94   573.3 1220.61   598.3 1234.31   618.2  1246.2   638.2 1256.28
#Mann= 3 , 0 , 0
       0      .1       0   292.5    .045       0   307.5      .1       0
Bank Sta=292.5,307.5
XS Rating Curve= 0 ,0
Exp/Cntr=0.3,0.1

Type RM Length L Ch R = 1 ,163.4   ,161.6,157.2,153.1
XS GIS Cut Line= 3
     1727874.859       206952.27     1727827.714      206727.575
     1727772.543      206467.772
#Sta/Elev= 30
       0 1136.32      10 1136.01    44.9 1136.59    59.9 1135.74    74.9 1133.38
    79.9 1133.27    99.8 1128.93   119.8 1122.54   129.8 1118.44   139.8 1115.11
   149.7 1110.52   164.7 1100.58   169.7 1098.54   179.7 1096.28   194.6 1094.91
   239.4 1093.82   249.3 1094.11   259.1 1095.62   267.7  1094.1   273.8 1093.39
   282.7 1094.54   293.5 1096.55   313.2 1097.18   318.1 1098.77     328 1104.98
   367.3 1124.27   401.7 1143.19   436.2 1160.26   470.6 1176.29   495.2  1185.8
#Mann= 3 , 0 , 0
       0      .1       0   267.7    .045       0   282.7      .1       0
Bank Sta=267.7,282.7
XS Rating Curve= 0 ,0
Exp/Cntr=0.3,0.1

Type RM Length L Ch R = 1 ,6.3     ,7.2,6.3,5.3
XS GIS Cut Line= 4
     1728013.654      207036.048     1727988.501      206686.927
      1727941.19      206571.248      1727790.51      206247.703
#Sta/Elev= 30
       0 1160.34      69 1124.15    83.8 1117.57    98.6 1112.48   118.3 1108.35
     143 1104.69   172.6 1101.97   187.3 1099.23   207.1 1094.34   216.9 1093.72
   231.7 1090.86   246.5 1090.39   271.2 1092.44   305.7 1093.12     350 1092.37
     365 1093.18   414.9 1091.97   429.9 1091.85     460 1094.69   494.8 1095.69
   509.7 1101.54   534.5 1113.54   574.2 1125.33     594 1130.46   658.4 1144.94
     708 1154.41   752.6 1161.07   777.4 1163.52   797.2  1167.1   831.9 1175.64
#Mann= 3 , 0 , 0
       0      .1       0   414.9    .045       0   429.9      .1       0
#XS Ineff= 2 , 0
           365.3 1093.15
Permanent Ineff=
       F       F
Bank Sta=414.9,429.9
XS Rating Curve= 0 ,0
Exp/Cntr=0.3,0.1

Chan Stop Cuts=-1
Use User Specified Reach Order=0